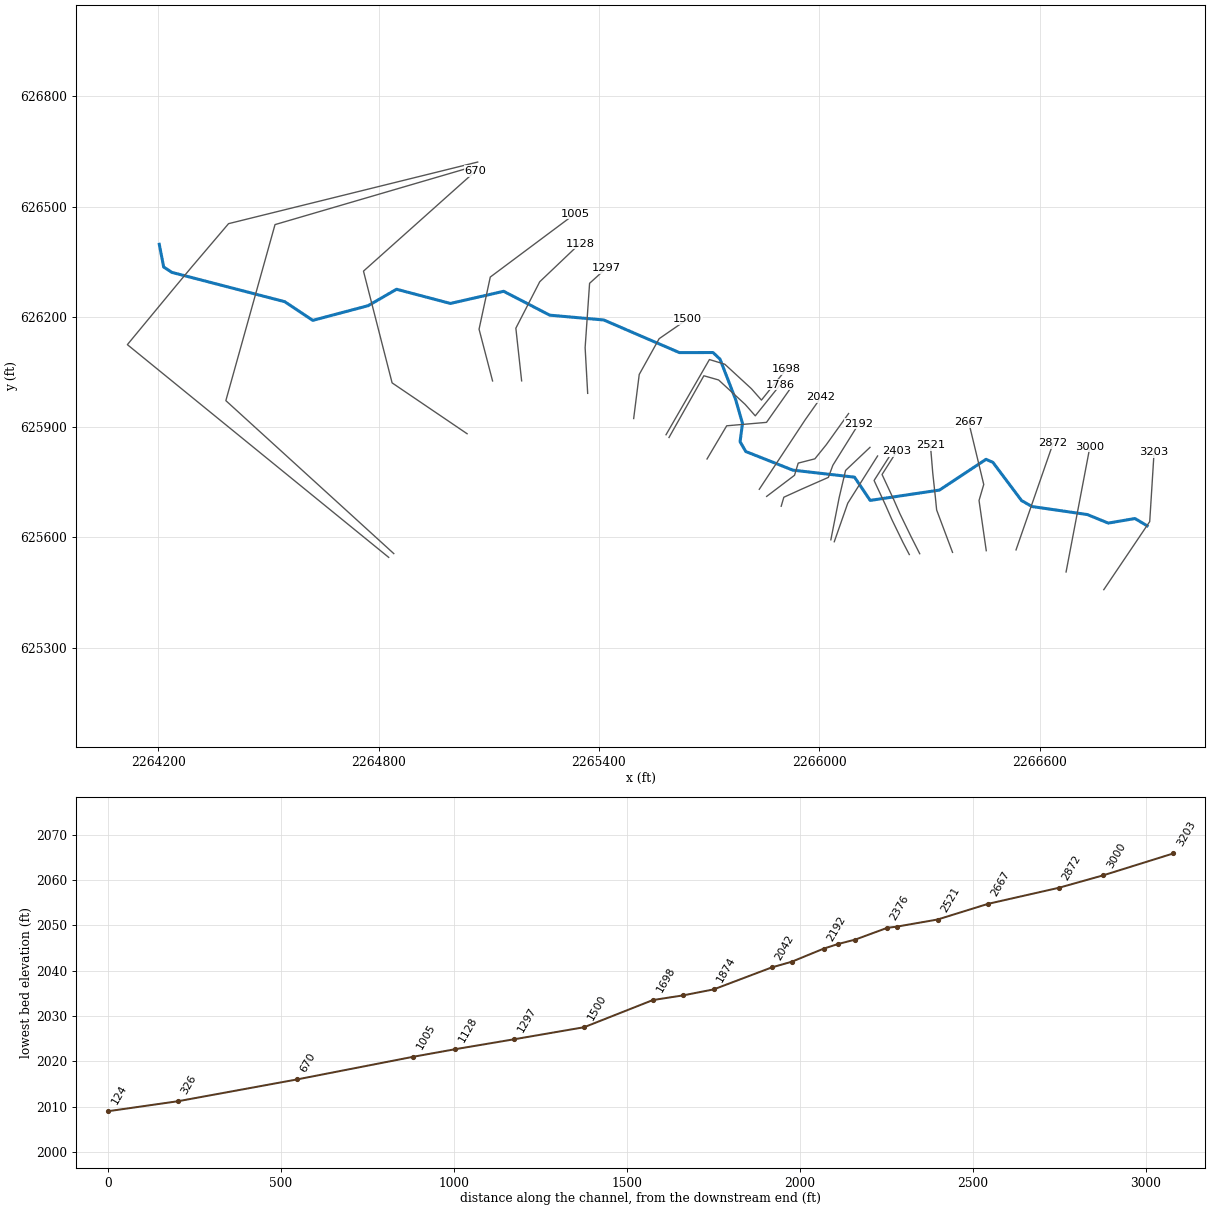
--- DNLEYRN.prj (project) ---

Proj Title=DNLEYRN
Current Plan=p01
Default Exp/Contr=0,0
English Units
Geom File=g01
Flow File=f01
Plan File=p01
BEGIN DESCRIPTION:
----------MODEL BY WOOD PLC 2022----------
AFH study
Randolph County, WV
HEC-RAS Version: RAS 6.2
Vertical Datum: NAVD88
Projection: NAD 1983 StatePlane West Virginia S FIPS 4702 (US Feet)
Terrain: 1-meter LIDAR (FEMA Region III 3DEP collected 2016-2018)
Land Use: 2019 NLCD
Hydrologic Method:
WV SIR2010-5033 regression equations
Additional Model Notes:
None
END DESCRIPTION:
DSS Export Rating Curves= 0
DSS Export Rating Curve Sorted= 0
DSS Export Volume Flow Curves= 0
DXF OffsetX= 0
DXF OffsetY= 0
DXF ScaleX= 0
DXF ScaleY= 0

--- DNLEYRN.p01 (plan) ---

Plan Title=Floodplain
Program Version=6.20
Geom File=g01
Flow File=f01
Subcritical Flow
K Sum by GR= 0
Std Step Tol= 0.01
Critical Tol= 0.01
Num of Std Step Trials= 20
Max Error Tol= 0.3
Flow Tol Ratio= 0.001
Split Flow NTrial= 30
Split Flow Tol= 0.02
Split Flow Ratio= 0.02
Log Output Level= 0
Friction Slope Method= 1
Unsteady Friction Slope Method= 2
Unsteady Bridges Friction Slope Method= 1
Parabolic Critical Depth
Global Vel Dist= 0 , 0 , 0
Global Log Level= 0
CheckData=False
Encroach Param=-1 ,0,0, 0
Mapping Interval=1HOUR
Computation Time Step Use Courant=        0
Computation Time Step Use Time Series=    0
Computation Time Step Count To Double=0
Computation Time Step Max Doubling=0
Computation Time Step Max Halving=0
Computation Time Step Residence Courant=0
Run HTab= 0
Run UNet= 0
Run Sediment= 0
Run PostProcess= 0
Run WQNet= 0
Run RASMapper= 0
UNET Theta= 0
UNET Theta Warmup= 0
UNET ZTol= 0
UNET ZSATol= 0
UNET MxIter= 0
UNET Max Iter WO Improvement= 0
UNET MaxInSteps= 0
UNET DtIC= 0
UNET DtMin= 0
UNET MaxCRTS= 0
UNET WFStab= 0
UNET SFStab= 0
UNET WFX= 1
UNET SFX= 1
UNET Gravity=32.174
UNET 1D Methodology=Finite Difference
UNET DSS MLevel= 1
UNET Pardiso=0
UNET DZMax Abort= 0
UNET Use Existing IB Tables= 0
UNET Froude Reduction=False
UNET Froude Limit= 0
UNET Froude Power= 0
UNET D1 Cores= 0
UNET WindReference=Eulerian
UNET WindDragFormulation=Hsu (1988)
UNET D2 Coriolis=0
UNET D2 Cores= 0
UNET D2 Theta= 1
UNET D2 Theta Warmup= 1
UNET D2 Z Tol= 0.01
UNET D2 Volume Tol= 0.01
UNET D2 Max Iterations= 20
UNET D2 Equation= 0
UNET D2 RampUpFraction=0.1
UNET D2 TimeSlices= 1
UNET D2 Turbulence Formulation=Non-Conservative (original)
UNET D2 Eddy Viscosity=0.3
UNET D2 Transverse Eddy Viscosity=0.1
UNET D2 Smagorinsky Mixing=0
UNET D2 BCVolumeCheck=0
UNET D2 Cores=0
UNET D2 SolverType=PARDISO (Direct)
UNET D2 Minimum Iterations= 2147483647
UNET D2 Maximum Iterations= 2147483647
UNET D2 Restart Number= 10
UNET D2 Relaxation Coeff=1.3
UNET D2 SOR Precondition Iterations= 10
UNET D2 ILUT Maximum Fill= 8
UNET D2 ILUT Tolerance=1E-08
UNET D1D2 MaxIter= 0
UNET D1D2 ZTol=0.01
UNET D1D2 QTol=0.1
UNET D1D2 MinQTol=1
Write IC File= 0
Write IC File at Fixed DateTime=0
Write IC File at Sim End=0
Echo Input=False
Echo Parameters=False
Echo Output=False
Write Detailed= 0
HDF Write Warmup=0
HDF Write Time Slices=0
HDF Flush=0
HDF Compression= 1
HDF Chunk Size= 1
HDF Spatial Parts= 1
HDF Use Max Rows=0
HDF Fixed Rows= 1
Calibration Method= 0
Calibration Iterations= 20
Calibration Max Change=0.05
Calibration Tolerance=0.2
Calibration Maximum=1.5
Calibration Minimum=0.5
Calibration Optimization Method= 1
WQ AD Non Conservative
WQ ULTIMATE=-1
WQ Max Comp Step=1HOUR
WQ Output Interval=15MIN
WQ Output Selected Increments= 0
WQ Output face flow=0
WQ Output face velocity=0
WQ Output face area=0
WQ Output face dispersion=0
WQ Output cell volume=0
WQ Output cell surface area=0
WQ Output cell continuity=0
WQ Output cumulative cell continuity=0
WQ Output face conc=0
WQ Output face dconc_dx=0
WQ Output face courant=0
WQ Output face peclet=0
WQ Output face adv mass=0
WQ Output face disp mass=0
WQ Output cell mass=0
WQ Output cell source sink temp=0
WQ Output nsm pathways=0
WQ Output nsm derived pathways=0
WQ Create Restart=0
WQ Fixed Restart=0
WQ System Summary=0
WQ Write To DSS=0
Sorting and Armoring Iterations= 10
XS Update Threshold= 0.02
Bed Roughness Predictor= 0
Hydraulics Update Threshold= 0.02
Energy Slope Method= 1
Volume Change Method= 1
Sediment Retention Method= 0
Sediment TS Multiplier= 1
Warm Up Method= 0
XS Weighting Method= 0
Number of US Weighted Cross Sections= 1
Number of DS Weighted Cross Sections= 1
Upstream XS Weight=0
Main XS Weight=1
Downstream XS Weight=0
Number of DS XS's Weighted with US Boundary= 1
Upstream Boundary Weight= 1
Weight of XSs Associated with US Boundary= 0
Number of US XS's Weighted with DS Boundary= 1
Downstream Boundary Weight= 0.5
Weight of XSs Associated with DS Boundary= 0.5
Percentile Method= 0
Sediment Output Level= 3
Mass or Volume Output= 0
Output Increment Type= 1
Profile and TS Output Increment= 1
Transport Output Increment 1
XS Output Flag= 0
XS Output Increment= 10
Read HDF5 Sediment Hotstart= 0
Sediment Hotstart Type= 0
Write Gradation File= 0
Read Gradation Hotstart= 0
Write HDF5 File= 1
Write Binary Output= 1
Write DSS Sediment File= 0
DSS Sediment Output Type= 1
SV Curve= 0
Specific Gage Flag= 0
Subcell Erosion Methods= 0
Subcell Deposition Methods= 0
Advection Scheme= 1
Matrix Solver= 0
Implicit Weighting Factor= 1
Maximum Outer Loop Convergence Iterations= 5
Convergence Maximum Absolute= 0.001
Convergence RMSE= 0.0001
Grain Fractions Max Abs Error= 0.001
Max Subgrid Regions= 1
Max Subgrid Length Scale= 3.402823E+38
Initial Layer Thickness= 3.402823E+38
Min Layer Thickness= 3.402823E+38
Max Layer Thickness= 3.402823E+38
Number of Layers= 5

--- DNLEYRN.f01 (steady flow) ---

Flow Title=Flow
Program Version=6.20
Number of Profiles= 1
Profile Names=P100yr
River Rch & RM=DNLEYRN,Main            ,3203
     494
Boundary for River Rch & Prof#=DNLEYRN,Main            , 1
Up Type= 0
Dn Type= 3
Dn Slope=0.01187
DSS Import GetInterval= 0
DSS Import GetPeak= 0
DSS Import FillOption= 0

--- DNLEYRN.g01 (geometry) ---

Geom Title=Geometry
Program Version=6.20

River Reach=DNLEYRN         ,Main
Reach XY= 30
2266891.77743796625631.250035852     2266858.633625651.076000005
2266786.06300001 625638.576000022266729.11900002625661.840000004
2266578.42400002625683.7150000042266549.95200004625700.034000009
2266472.17400001625803.8540000022266453.42400002625812.187000021
2266326.68800004625728.5069999992266138.14600003625700.382000029
2266095.43800001625763.5760000052265927.73000002625782.673000008
2265799.60500003625833.3680000162265783.98000002625860.104000017
2265790.57699999625910.1040000022265771.48000002625976.076000005
2265729.46600001626084.7570000142265710.36900003626102.812000021
     2265618.921626102.6009999962265413.14700003626191.354000032
     2265265.924 626204.549000012265140.57699999626269.479000017
2264995.54799999626236.4110000132264849.08400001626275.034999996
2264771.48000003626230.243000016      2264620.98626190.386000022
2264544.48181859626241.270240828     2264237.799626320.868000016
2264215.24318269626335.5399401042264203.22700003626397.412000015

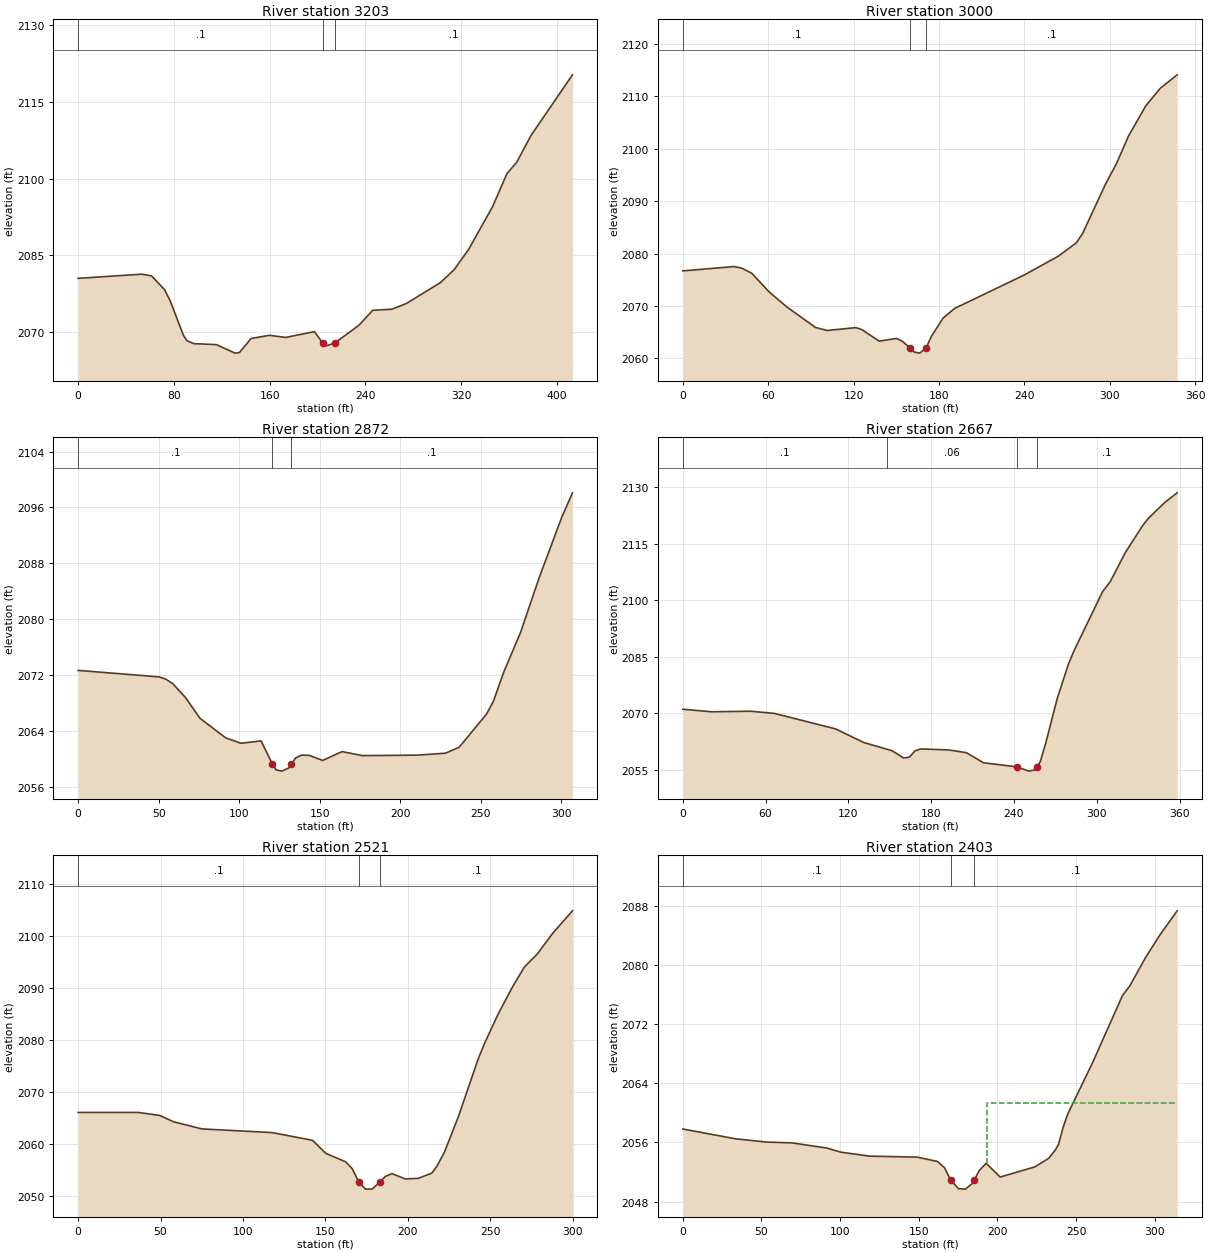
Type RM Length L Ch R = 1 ,3203    ,202.8,202.8,202.8
XS GIS Cut Line= 3
2266773.91812419625457.4152792142266898.90959896625642.726742662
2266910.77926757625831.756546629
#Sta/Elev= 30
       0 2080.48    53.3  2081.3    61.3 2080.97    72.1 2078.29    76.9 2076.08
    87.9 2069.35    90.8 2068.28    96.5  2067.7   115.5  2067.5   131.1 2065.84
   134.8 2065.97   144.5 2068.71   159.9 2069.33   173.4 2068.91   197.4 2070.05
   204.3 2067.81   207.2 2067.27  214.31 2067.81   234.6  2071.3     246 2074.22
   262.1 2074.44   274.1 2075.55   302.5 2079.63   313.8  2082.1   326.2 2086.15
   346.2 2094.53   358.2    2101   366.3  2103.2   378.3 2108.46   412.9 2120.33
#Mann= 3 ,-1,0
       0      .1       0   204.3    .045       0  214.31      .1       0
Bank Sta=204.3,214.31
XS Rating Curve= 0 ,0
Exp/Cntr(USF)=0,0
Exp/Cntr=0.3,0.1

Type RM Length L Ch R = 1 ,3000    ,128.3,128.3,128.3
XS GIS Cut Line= 2
 2266671.2530001625505.6167871622266736.26195879625846.879797621
#Sta/Elev= 30
       0  2076.7    36.2 2077.53    41.5 2077.21    48.4 2076.26    60.6 2072.71
    72.8 2069.88    93.2 2065.91   101.4 2065.33   121.7 2065.88   125.8  2065.5
     138  2063.3   150.2 2063.81   154.3 2063.27  159.47 2062.04   162.4 2061.24
   166.5 2061.01  171.04 2062.04   174.6 2064.16   182.8 2067.66   190.9 2069.52
   239.8  2075.9   263.8 2079.49   276.4 2082.02   280.9  2083.8   296.8 2093.12
   304.8  2097.2   313.1 2102.37   325.3 2108.18   335.6 2111.56   347.4 2114.11
#Mann= 3 ,-1,0
       0      .1       0  159.47    .045       0  171.04      .1       0
Bank Sta=159.47,171.04
XS Rating Curve= 0 ,0
Exp/Cntr(USF)=0,0
Exp/Cntr=0.3,0.1

Type RM Length L Ch R = 1 ,2872    ,205.1,205.1,205.1
XS GIS Cut Line= 2
2266535.06203063625565.6662755432266635.86096479 625855.61152084
#Sta/Elev= 30
       0 2072.68    50.3 2071.75    54.5 2071.43    58.8 2070.77    66.5 2068.85
    75.7 2065.82    91.6 2063.03   101.1 2062.25   113.6 2062.59   120.7 2059.25
     123 2058.44   126.5 2058.26   130.8 2058.71   132.5 2059.26     135 2060.13
   138.8 2060.55   143.5 2060.52   151.9 2059.79   163.9 2061.06   176.5 2060.48
     211 2060.55   228.2 2060.83   236.6 2061.67   253.6 2066.42   257.8 2068.21
   264.5 2072.54   274.7 2078.08   286.4    2086   300.2 2094.51     307  2098.1
#Mann= 3 ,-1,0
       0      .1       0   120.7    .045       0   132.5      .1       0
Bank Sta=120.7,132.5
XS Rating Curve= 0 ,0
Exp/Cntr(USF)=0,0
Exp/Cntr=0.3,0.1

Type RM Length L Ch R = 1 ,2667    ,145.6,145.6,145.6
XS GIS Cut Line= 4
2266454.01316028625563.4688555952266434.37050853625700.113389543
2266447.18093359625743.668834739 2266406.1875734625913.620473837
#Sta/Elev= 30
       0 2071.11    20.8 2070.43    49.1 2070.58    66.4    2070   110.8 2065.89
     131 2062.31   151.7 2060.11     160  2058.2   164.2  2058.4   168.3 2060.09
   172.5 2060.59   193.2 2060.31   205.6 2059.59   217.9 2056.93  242.092055.844
   250.8 2054.71     255 2055.02  256.652055.845   259.1 2057.22   263.2 2062.34
   271.4    2074   279.6 2083.17   283.8 2086.81   304.3 2102.28   309.9 2104.98
   320.8 2112.66   333.1 2119.65   337.2  2121.6   349.5 2125.95   358.3 2128.44
#Mann= 4 ,-1,0
       0      .1       0  148.05     .06       0  242.09    .045       0
  256.65      .1       0
Bank Sta=242.09,256.65
XS Rating Curve= 0 ,0
Exp/Cntr(USF)=0,0
Exp/Cntr=0.3,0.1

Type RM Length L Ch R = 1 ,2521    ,118.6,118.6,118.6
XS GIS Cut Line= 5
2266362.22303809625558.9266900692266318.97831908625674.355251005
 2266314.7844571625716.2848527082266308.46003025625774.258765484
 2266302.1356034625850.151887664
#Sta/Elev= 30
       0 2066.03    36.6 2066.03    49.4 2065.46    57.9 2064.24      75 2062.86
   117.7 2062.15   142.2 2060.66   150.2 2058.16   162.3 2056.52   166.3 2055.19
  170.16 2052.71   174.3 2051.26   178.4 2051.29  183.432052.711   186.4 2053.72
   190.4 2054.24   198.5 2053.22   206.5 2053.34   214.6 2054.35   217.7 2055.68
   222.2 2058.36   230.7 2065.23   242.7 2076.33   246.7 2079.43   254.7 2084.91
   263.7  2090.3   270.8 2094.07   278.6 2096.56   287.9 2100.53   299.9 2104.86
#Mann= 3 ,-1,0
       0      .1       0  170.16    .045       0  183.43      .1       0
Bank Sta=170.16,183.43
XS Rating Curve= 0 ,0
Exp/Cntr(USF)=0,0
Exp/Cntr=0.3,0.1

Type RM Length L Ch R = 1 ,2403    ,26.7,26.7,26.7
XS GIS Cut Line= 6
2266272.93080234625555.2557740272266248.86814377625602.717828114
 2266218.8931593625664.4185205812266202.02802104625702.892117242
 2266170.4058868625770.8797058612266210.91274319625834.522841621
#Sta/Elev= 30
       0 2057.83    33.5  2056.5    53.2 2056.06    69.3 2055.95    91.5 2055.25
   100.4 2054.69   118.9 2054.15   148.8 2054.02   161.9 2053.43   166.3 2052.59
   170.22050.921   175.2 2049.74   179.6 2049.68     184 2050.44  185.27 2050.92
   188.4 2052.19   192.8 2053.19   201.7 2051.32   223.7 2052.69   232.5 2053.85
   236.9 2055.02   238.8 2055.75   241.7 2058.04   244.6 2059.83   260.5 2066.85
   279.4  2075.9   284.2 2077.26   294.2  2081.1   303.2 2084.12   314.2  2087.4
#Mann= 3 ,-1,0
       0      .1       0   170.2    .045       0  185.27      .1       0
#XS Ineff= 2 , 0
                           193.1         2061.36
Permanent Ineff=
       F       F
Bank Sta=170.2,185.27
XS Rating Curve= 0 ,0
Exp/Cntr(USF)=0,0
Exp/Cntr=0.3,0.1

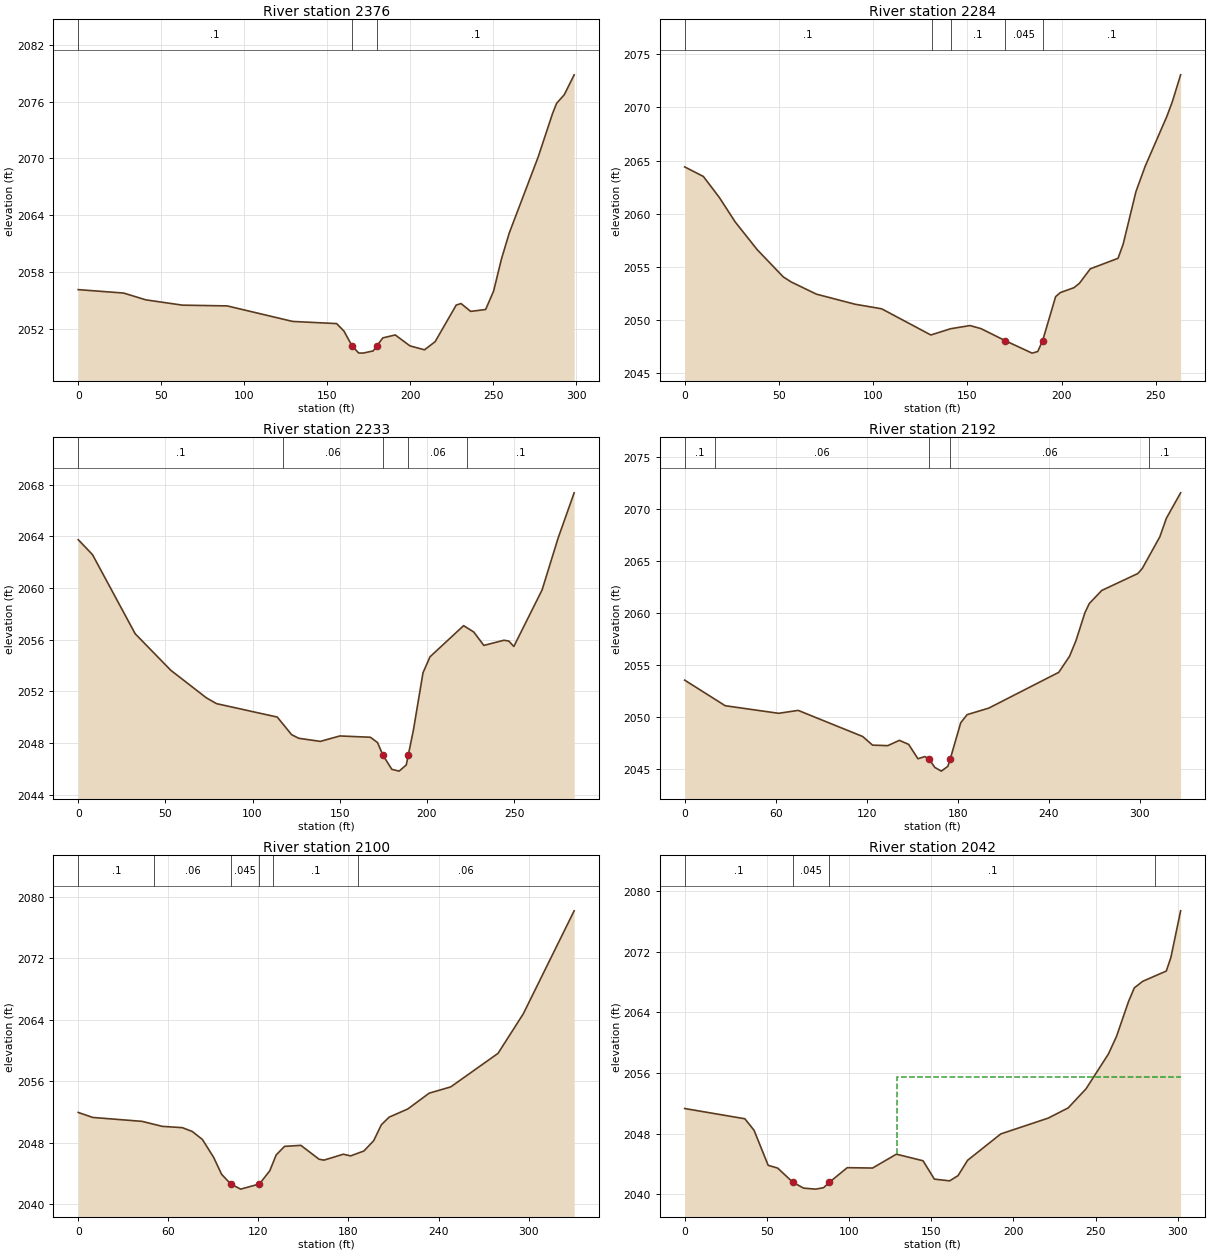
Type RM Length L Ch R = 1 ,2376    ,92.3,92.3,92.3
XS GIS Cut Line= 6
2266244.57448423625553.0170248472266227.18930852625586.332661937
2266197.21432405625648.0333544042266180.34918579625686.506951064
2266148.72705155625754.4945396842266189.23390794625818.137675444
#Sta/Elev= 30
       0 2056.14    27.3 2055.78    40.7 2055.06    62.8  2054.5    89.7 2054.42
   129.1 2052.78   155.6 2052.55     160 2051.76   164.8 2050.22   168.8 2049.45
   171.4 2049.43   177.6 2049.66  179.94 2050.23   183.4 2051.04   190.9 2051.35
   199.7  2050.2   208.5 2049.78   214.9 2050.64   227.6 2054.51   230.5 2054.67
   236.3 2053.84   245.3 2054.04   250.1 2055.98   254.8 2059.36   259.5 2062.11
   276.9 2070.14   285.6 2074.75     288 2075.82   292.7 2076.75   298.6 2078.84
#Mann= 3 ,-1,0
       0      .1       0   164.8    .045       0  179.94      .1       0
Bank Sta=164.8,179.94
XS Rating Curve= 0 ,0
Exp/Cntr(USF)=0,0
Exp/Cntr=0.3,0.1

Type RM Length L Ch R = 1 ,2284    ,50.8,50.8,50.8
XS GIS Cut Line= 3
2266040.37630881625587.861381003 2266077.0769185625692.723620453
  2266158.215917625821.268040501
#Sta/Elev= 30
       0  2064.4     9.9  2063.5    18.3 2061.54    26.8 2059.21    38.5 2056.59
    52.3 2054.03    56.5 2053.55    69.9  2052.4    90.4 2051.45   104.5 2051.02
   130.6 2048.55   141.1 2049.14   151.4 2049.44   157.2 2049.15  170.122048.008
   184.3 2046.84   187.3 2046.99  189.89 2048.01   196.8 2052.17   199.3 2052.55
   206.5 2053.01   209.4 2053.42   215.2 2054.79   229.9 2055.78   232.6  2057.1
   239.4 2062.07   244.3 2064.46   255.8 2069.16   258.7 2070.54   263.1 2073.08
#Mann= 5 ,-1,0
       0      .1       0   131.1     .06       0   141.1      .1       0
  170.12    .045       0  189.89      .1       0
Bank Sta=170.12,189.89
XS Rating Curve= 0 ,0
Exp/Cntr(USF)=0,0
Exp/Cntr=0.3,0.1

Type RM Length L Ch R = 1 ,2233    ,40.7,40.7,40.7
XS GIS Cut Line= 4
2266031.05568487625593.101295882  2266053.741674625708.125274551
2266071.09263929625781.866877035 2266137.6046729625844.764126213
#Sta/Elev= 30
       0 2063.74     8.2 2062.58    32.7 2056.46    53.1 2053.64    73.5 2051.51
    79.3 2051.06   114.2 2050.02   122.4 2048.66   126.5 2048.38   138.9 2048.14
   150.1 2048.56   167.6 2048.46   171.7 2048.05  174.832047.069   179.9 2045.98
   184.1 2045.84   188.2 2046.32  189.322047.067   192.3 2049.02   197.8 2053.45
   201.8 2054.68   221.1 2057.09   226.9  2056.6   232.7 2055.56   244.2 2055.96
     247  2055.9   249.9 2055.48   266.1 2059.85   275.3 2063.86   284.5 2067.36
#Mann= 5 ,-1,0
       0      .1       0  117.24     .06       0  174.83    .045       0
  189.32     .06       0     223      .1       0
Bank Sta=174.83,189.32
XS Rating Curve= 0 ,0
Exp/Cntr(USF)=0,0
Exp/Cntr=0.3,0.1

Type RM Length L Ch R = 1 ,2192    ,92,92,92
XS GIS Cut Line= 6
2265895.91486756625684.4980476432265903.12954591625709.010997629
2265951.00186865625730.782133151 2266024.3833935625763.071085447
2266036.54678965625796.0627650272266107.10577253625909.163662195
#Sta/Elev= 30
       0 2053.59    26.7 2051.13    61.9  2050.4    74.8 2050.68   117.3 2048.17
   123.8 2047.34   133.8 2047.29   141.5  2047.8   147.6 2047.41   153.7 2046.03
   158.3 2046.24  161.182045.984   164.8  2045.2   169.1 2044.84   173.4  2045.3
  174.942045.985   181.9 2049.49   186.1 2050.27   200.4  2050.9   246.5 2054.34
   253.6 2055.88   257.9 2057.41   263.7 2060.06   266.6 2060.95   274.8 2062.21
   298.6 2063.84   301.5 2064.32   313.1 2067.37   317.4 2069.15   326.8  2071.6
#Mann= 5 ,-1,0
       0      .1       0      20     .06       0  161.18    .045       0
  174.94     .06       0  305.72      .1       0
Bank Sta=161.18,174.94
XS Rating Curve= 0 ,0
Exp/Cntr(USF)=0,0
Exp/Cntr=0.3,0.1

Type RM Length L Ch R = 1 ,2100    ,58.3,58.3,58.3
XS GIS Cut Line= 6
2265856.31015981 625711.248208572265932.17002864625768.720378644
2265942.23220493625801.8703308422265987.59159513625813.514402159
 2266018.7028887625852.0806121222266079.32613489625936.756405856
#Sta/Elev= 30
       0 2051.93     9.7 2051.28    42.5 2050.77      56 2050.12    69.4 2049.95
      76 2049.45    82.7 2048.42    90.2 2046.09    95.5 2043.89  101.59 2042.63
   108.2 2041.96   120.7 2042.63   127.6 2044.35   131.8 2046.39   137.4 2047.52
   148.3 2047.65   160.4 2045.85   163.7 2045.73   176.6  2046.5   181.4 2046.28
   190.3 2046.92   196.8 2048.26   201.9 2050.33   207.1 2051.32   219.5 2052.38
   233.8 2054.44   248.1 2055.25   279.6 2059.61   296.4 2064.74   330.3 2078.14
#Mann= 6 ,-1,0
       0      .1       0   50.77     .06       0  101.59    .045       0
   120.7     .06       0  129.82      .1       0  186.65     .06       0
Bank Sta=101.59,120.7
XS Rating Curve= 0 ,0
Exp/Cntr(USF)=0,0
Exp/Cntr=0.3,0.1

Type RM Length L Ch R = 1 ,2042    ,167.7,167.7,167.7
XS GIS Cut Line= 3
2265836.25501508625730.6566244832265960.99460384625919.429206739
2266004.44143618625981.094916253
#Sta/Elev= 30
       0 2051.32    36.6 2049.97    42.2 2048.45    50.8 2043.83    56.6 2043.46
   65.852041.587    72.4 2040.82    79.7 2040.69    84.5 2040.88      882041.587
    98.9 2043.52   114.3 2043.47   128.8  2045.3     145 2044.43   151.9 2042.01
   161.2 2041.78   166.3 2042.47   172.1 2044.49   192.3 2047.97   221.2 2050.06
   233.3  2051.4   244.2 2053.93   257.8 2058.52   262.7 2060.83     270 2065.42
   273.5 2067.22   278.6 2068.09     293 2069.45   295.8 2071.26   301.7 2077.39
#Mann= 4 ,-1,0
       0      .1       0   65.85    .045       0      88      .1       0
  286.26     .06       0
#XS Ineff= 2 , 0
                           129.4         2055.53
Permanent Ineff=
       F       F
Bank Sta=65.85,88
XS Rating Curve= 0 ,0
Exp/Cntr(USF)=0,0
Exp/Cntr=0.3,0.1

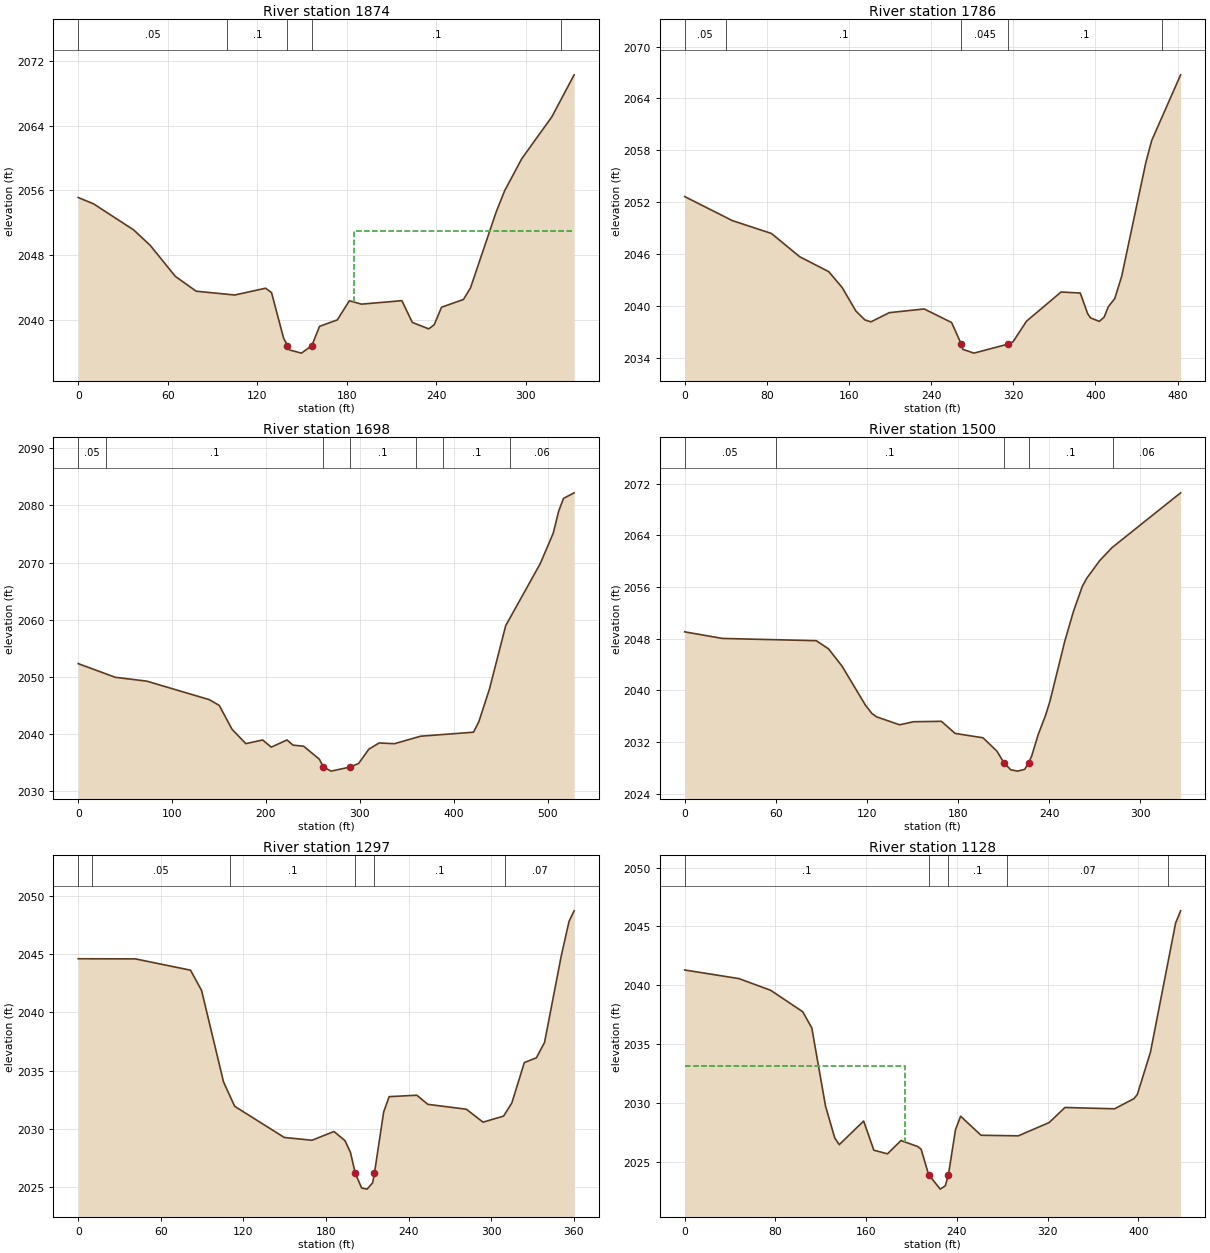
Type RM Length L Ch R = 1 ,1874    ,87.7,87.7,87.7
XS GIS Cut Line= 4
2265694.04831608625813.1442833382265747.59076865 625903.41934872
2265855.92084711625912.7581485882265924.40537947626009.881667205
#Sta/Elev= 30
       0  2055.1    10.3 2054.32    37.2 2051.09    48.3 2049.18    65.1 2045.35
    79.1 2043.51     105 2043.04   125.6 2043.88   129.6 2043.34   137.7  2037.7
  140.272036.783   141.7 2036.24   149.7 2035.85  156.652036.784   161.8 2039.16
   173.7 2039.96   181.8 2042.33   189.9 2041.91     217 2042.34     224 2039.65
     235 2038.85   238.7 2039.37   243.6 2041.53   258.3 2042.49     263 2043.92
   280.2  2053.3   285.9 2055.94   297.4 2059.91   317.5 2065.07   332.5 2070.28
#Mann= 5 ,-1,0
       0     .05       0     100      .1       0  140.27    .045       0
  156.65      .1       0  323.69     .06       0
#XS Ineff= 2 , 0
                          184.99         2050.93
Permanent Ineff=
       F       F
Bank Sta=140.27,156.65
XS Rating Curve= 0 ,0
Exp/Cntr(USF)=0,0
Exp/Cntr=0.3,0.1

Type RM Length L Ch R = 1 ,1786    ,88,88,88
XS GIS Cut Line= 6
  2265590.579005625871.6216996422265685.44954106626039.574956619
2265725.59593625626028.1350407762265797.89162496625961.623007162
2265825.36398667625930.5358610172265893.32193406626015.121816808
#Sta/Elev= 30
       0 2052.65    46.4 2049.87    84.5 2048.38     112 2045.69   140.3 2043.96
   153.4 2042.12   166.7 2039.41   175.5 2038.38   181.4 2038.16   199.2 2039.22
   233.2 2039.65   259.9 2038.08  269.412035.568   270.8 2034.98   281.6 2034.54
  314.442035.569   319.7 2035.85   332.9 2038.24   366.5 2041.61   385.2 2041.49
   392.5 2039.07   395.3 2038.61   403.8 2038.21   408.5 2038.72   412.4 2039.89
   418.8 2040.86   425.5 2043.42   449.1 2056.62   454.7 2059.12   482.9 2066.73
#Mann= 5 ,-1,0
       0     .05       0      40      .1       0  269.41    .045       0
  314.44      .1       0  464.36     .06       0
Bank Sta=269.41,314.44
XS Rating Curve= 0 ,0
Exp/Cntr(USF)=0,0
Exp/Cntr=0.3,0.1

Type RM Length L Ch R = 1 ,1698    ,198.6,198.6,198.6
XS GIS Cut Line= 6
 2265582.4859597625879.0865427952265700.55486277626083.737178038
2265742.40635727626071.0250647582265814.70204598626004.513031144
2265842.17440769625973.4258849992265910.13235508 626058.01184079
#Sta/Elev= 30
       0 2052.31    39.4 2049.92    73.1 2049.24   139.5 2046.01   150.2    2045
   163.8 2040.83   178.5 2038.31   196.4 2038.95   205.6  2037.7   222.4 2038.95
   228.7 2038.05   240.1 2037.86   256.8 2035.59   261.22034.217   269.3  2033.5
  289.692034.217   298.7 2034.85   309.6 2037.35   320.5 2038.43   336.8  2038.3
   364.7 2039.61     421 2040.31   426.7 2042.15     438 2047.86   455.3 2058.95
   492.1 2069.81   505.9 2075.12   511.8 2079.02   516.9 2081.22   528.2 2082.19
#Mann= 7 ,-1,0
       0     .05       0      30      .1       0   261.2    .045       0
  289.69      .1       0  360.01     .06       0  388.24      .1       0
  459.73     .06       0
Bank Sta=261.2,289.69
XS Rating Curve= 0 ,0
Exp/Cntr(USF)=0,0
Exp/Cntr=0.3,0.1

Type RM Length L Ch R = 1 ,1500    ,203.1,203.1,203.1
XS GIS Cut Line= 4
2265494.38712939625923.1466103092265509.53904366626043.182163435
2265563.71038955 626140.482890662265641.36131446626194.035252668
#Sta/Elev= 30
       0 2049.06    24.9 2048.04    86.7 2047.69    94.8 2046.42   103.7 2043.74
     119 2037.75   123.3 2036.44   126.4 2035.91   141.6 2034.68   150.7 2035.15
   169.1 2035.22   178.2 2033.34   196.5 2032.67   205.7  2030.6  210.292028.805
   214.8 2027.72   219.4 2027.51     224 2027.79  226.532028.807   228.6 2029.85
   232.9 2033.18   237.8 2036.19   240.6 2038.31   250.4 2047.62   256.2 2052.29
   261.9 2056.07   264.8 2057.33   273.4 2060.08   281.5 2062.09   326.7 2070.57
#Mann= 5 ,-1,0
       0     .05       0      60      .1       0  210.29    .045       0
  226.53      .1       0  282.35     .06       0
Bank Sta=210.29,226.53
XS Rating Curve= 0 ,0
Exp/Cntr(USF)=0,0
Exp/Cntr=0.3,0.1

Type RM Length L Ch R = 1 ,1297    ,168.8,168.8,168.8
XS GIS Cut Line= 4
2265369.22230432  625991.69756882265362.29927776626116.068251371
2265374.42018274626291.2704233722265418.98593438626331.551006591
#Sta/Elev= 30
       0 2044.59    41.5 2044.58    81.6 2043.61    89.6 2041.88   105.6 2034.02
   113.7 2031.94   149.7 2029.27   169.8 2029.03   185.8 2029.78   193.8    2029
   197.8 2027.98  201.332026.182   205.9 2024.94   209.9 2024.84   213.9 2025.38
  215.192026.185   221.9 2031.45   225.9 2032.77     246 2032.89     254 2032.11
     282 2031.69   294.1 2030.58     309  2031.1     315 2032.22   324.1 2035.69
   332.9  2036.1   338.8 2037.42   350.9 2044.82   356.6  2047.8   360.3  2048.7
#Mann= 6 ,-1,0
       0     .08       0      10     .05       0     110      .1       0
  201.33    .045       0  215.19      .1       0  310.18     .07       0
Bank Sta=201.33,215.19
XS Rating Curve= 0 ,0
Exp/Cntr(USF)=0,0
Exp/Cntr=0.3,0.1

Type RM Length L Ch R = 1 ,1128    ,122.8,122.8,122.8
XS GIS Cut Line= 4
2265189.47543935626025.7038088622265173.74191153626169.075557818
2265238.77763904626295.4674887232265348.15146177626399.535864824
#Sta/Elev= 30
       0  2041.3    47.8 2040.57    75.9 2039.57   104.1 2037.75   112.1 2036.37
   124.2 2029.73   132.3 2027.03   136.3 2026.45   157.8 2028.46   166.8 2025.98
   178.8 2025.67   190.7  2026.8   205.5 2026.29   208.5 2026.06  215.082023.907
   225.3 2022.67   229.8 2022.95  232.582023.907   238.8 2027.72   243.3 2028.87
   261.3 2027.25   294.2  2027.2   321.4 2028.33   335.3 2029.61   379.1  2029.5
   396.1 2030.36   399.1 2030.71   410.7 2034.31   432.9 2045.29   437.3 2046.33
#Mann= 5 ,-1,0
       0      .1       0  215.08    .045       0  232.58      .1       0
  284.23     .07       0  426.38     .05       0
#XS Ineff= 2 , 0
          194.18 2033.15
Permanent Ineff=
       F       F
Bank Sta=215.08,232.58
XS Rating Curve= 0 ,0
Exp/Cntr(USF)=0,0
Exp/Cntr=0.3,0.1

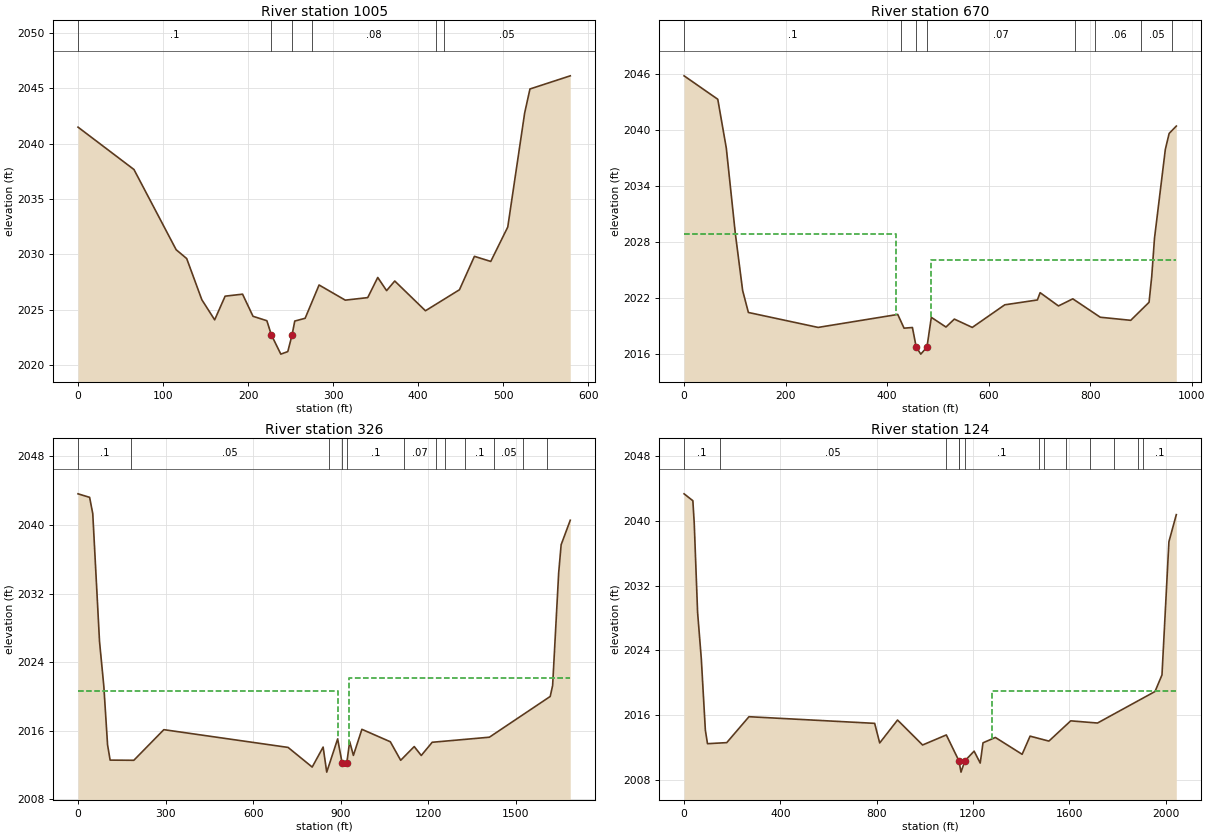
Type RM Length L Ch R = 1 ,1005    ,335.4,335.4,335.4
XS GIS Cut Line= 4
2265110.37104977626025.4912912022265073.60046357626166.379216066
 2265104.1405616626308.2547603692265335.10031442626480.601563077
#Sta/Elev= 30
       0  2041.5    65.8 2037.67   115.4 2030.42   127.8 2029.62   145.6  2025.9
   160.7 2024.08     173 2026.22   193.5  2026.4   205.8  2024.4   222.1    2024
  227.412022.716   238.5 2020.98   246.7 2021.21  251.742022.715   254.9 2023.97
   267.1 2024.22   283.5 2027.23   314.3 2025.86   340.7 2026.09   352.5 2027.91
   362.9 2026.72   372.5 2027.59   408.6  2024.9   448.6  2026.8   466.2 2029.82
   485.4 2029.36   505.4 2032.47   525.3 2042.79   531.5 2044.95   578.9 2046.14
#Mann= 6 ,-1,0
       0      .1       0  227.41    .045       0  251.74      .1       0
  275.61     .08       0  420.73     .07       0  430.73     .05       0
Bank Sta=227.41,251.74
XS Rating Curve= 0 ,0
Exp/Cntr(USF)=0,0
Exp/Cntr=0.3,0.1

Type RM Length L Ch R = 1 ,670     ,343.6,343.6,343.6
XS GIS Cut Line= 4
2265041.05296943 625881.811728242264836.93160719626020.253624355
2264759.06079907626324.3538508092265064.28253785626596.992982938
#Sta/Elev= 30
       0 2045.79    66.4 2043.28    83.2 2038.05     101  2028.9   115.4  2022.8
   126.7 2020.45   264.1 2018.85     421 2020.24   433.4 2018.77   449.9 2018.84
  457.372016.741   466.4 2015.99  478.562016.742   487.1 2019.93     516 2018.89
   532.5 2019.74   567.8 2018.85   631.8 2021.27   696.1 2021.79   701.5 2022.57
   737.6 2021.15   765.9 2021.91     820 2019.94     880 2019.61   916.1 2021.54
   921.4 2024.32   926.8 2028.38   948.2 2037.92   955.7 2039.62   969.8 2040.41
#Mann= 8 ,-1,0
       0      .1       0  426.64     .07       0  457.37    .045       0
  478.56     .07       0  770.55     .05       0  810.55     .06       0
  900.55     .05       0  960.55      .1       0
#XS Ineff= 2 , 0
          418.32 2028.89  487.28         2026.12
Permanent Ineff=
       F       F
Bank Sta=457.37,478.56
XS Rating Curve= 0 ,0
Exp/Cntr(USF)=0,0
Exp/Cntr=0.3,0.1

Type RM Length L Ch R = 1 ,326     ,202.5,202.5,202.5
XS GIS Cut Line= 4
2264841.50446266625555.5963374612264384.46148158625971.896881684
2264518.27277281626451.0047388142265066.19354216626611.297307395
#Sta/Elev= 30
       0 2043.63    39.7 2043.22    50.5 2041.32    73.6 2026.44    88.4  2021.2
   101.2 2014.37     110 2012.59   191.2 2012.57     294 2016.14   719.7 2014.07
   802.3 2011.78   839.8 2014.11   852.1 2011.19   889.5 2015.06  904.52 2012.31
  921.072012.305   930.7 2014.75   943.5 2013.14   972.6 2016.18    1070 2014.73
  1105.5 2012.57  1151.9 2014.17    1176 2013.13  1213.5 2014.67  1409.4 2015.26
  1617.8 2020.01  1626.1 2021.29  1646.9 2034.46  1655.3  2037.7  1686.5 2040.55
#Mann= 12 ,-1,0
       0      .1       0     180     .05       0  858.22      .1       0
  904.52    .045       0  921.07      .1       0 1115.66     .07       0
 1225.66      .1       0 1255.66     .07       0 1325.66      .1       0
 1425.66     .05       0 1525.66     .06       0 1605.66      .1       0
#XS Ineff= 2 , 0
          889.32 2020.68     929         2022.14
Permanent Ineff=
       F       F
Bank Sta=904.52,921.07
XS Rating Curve= 0 ,0
Exp/Cntr(USF)=0,0
Exp/Cntr=0.3,0.1

Type RM Length L Ch R = 1 ,124     ,,,
XS GIS Cut Line= 6
2264827.66962439625545.3425660262264116.44593725626124.276693929
2264239.80808841 626273.526199952264290.38814978 626334.27962691
2264391.80198878626453.5650585212265069.91855794626621.277305776
#Sta/Elev= 30
       0 2043.33    36.5 2042.48    42.2  2039.7    56.1 2028.73    71.6 2022.97
    88.4 2014.16    97.3 2012.49   177.2 2012.62   269.6 2015.82   791.8    2015
   812.7 2012.58   886.8 2015.41   990.9 2012.33  1089.5 2013.57 1141.922010.371
  1150.5 2008.98 1166.55 2010.37  1204.9 2011.57  1230.3  2010.1  1241.9  2012.6
  1293.3 2013.26  1404.4 2011.18  1437.4 2013.42  1515.6 2012.81  1606.3 2015.31
  1717.5 2015.04  1956.5 2018.93  1985.4 2020.98  2014.2 2037.42  2044.9 2040.76
#Mann= 13 ,-1,0
       0      .1       0     150     .05       0 1087.06     .07       0
  1140.7      .1       0 1141.92    .045       0 1166.55      .1       0
 1476.32     .07       0 1496.32      .1       0 1586.32     .07       0
 1686.32      .1       0 1786.32     .05       0 1886.32     .06       0
 1906.32      .1       0
#XS Ineff= 2 , 0
                         1280.38         2019.02
Permanent Ineff=
       F       F
Bank Sta=1141.92,1166.55
XS Rating Curve= 0 ,0
Exp/Cntr(USF)=0,0
Exp/Cntr=0.3,0.1
LCMann Table=0

Chan Stop Cuts=-1
Use User Specified Reach Order=0
Composite Channel Slope=5